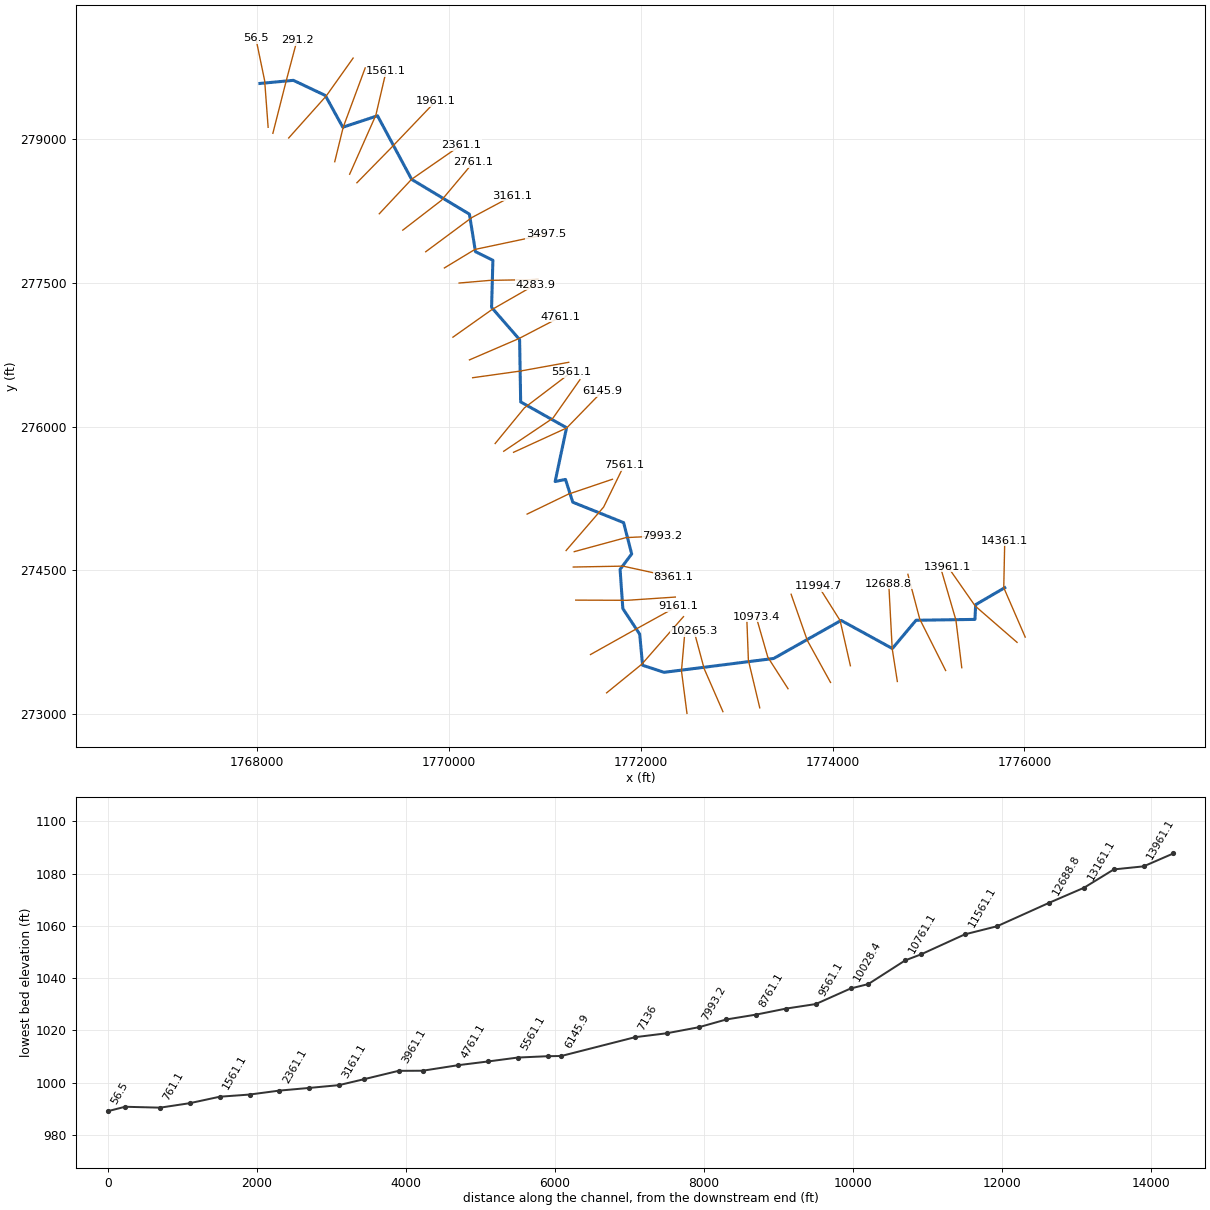
--- BeardRn.prj (project) ---

Proj Title=BeardRn
Current Plan=p01
Default Exp/Contr=0,0
English Units
Geom File=g01
Flow File=f01
Plan File=p01
BEGIN DESCRIPTION:
END DESCRIPTION:
DSS Export Rating Curves= 0
DSS Export Rating Curve Sorted= 0
DSS Export Volume Flow Curves= 0
DXF OffsetX= 0
DXF OffsetY= 0
DXF ScaleX= 0
DXF ScaleY= 0

--- BeardRn.p01 (plan) ---

Plan Title=Floodplain
Program Version=4.00
Geom File=g01
Flow File=f01
K Sum by GR=0
Std Step Tol=0.01
Critical Tol=0.01
Num of Std Step Trials=20
Max Error Tol=0.3
Flow Tol Ratio=0.001
Split Flow NTrial=30
Split Flow Tol=0.02
Split Flow Ratio=0.02
Log Output Level=0
Friction Slope Method=1
Unsteady Friction Slope Method=2
Unsteady Bridges Friction Slope Method=1
Global Log Level=0
CheckData=False
Run HTab=0
Run UNet=0
Run PostProcess=0
UNET Theta=0
UNET Theta Warmup=0
UNET ZTol=0
UNET ZSATol=0
UNET MxIter=0
UNET MaxInSteps=0
UNET DtIC=0
UNET DtMin=0
UNET MaxCRTS=0
UNET WFStab=0
UNET SFStab=0
UNET WFX=0
UNET SFX=0
UNET DSS MLevel=0
UNET DZMax Abort=0
UNET Convert EG Bridges=0
UNET Use Existing IB Tables=0
UNET Froude Limit=0
UNET Froude Power=0
Write IC File=0
Echo Input=False
Echo Output=False
Write Detailed=0

--- BeardRn.f01 (steady flow) ---

Flow Title=NFF Regression Equation
Program Version=4.00
Number of Profiles=1
Profile Names=P100yr
River Rch & RM=BeardRn,Main      ,14361.1
730.5429
River Rch & RM=BeardRn,Main      ,13961.1
759.9212
River Rch & RM=BeardRn,Main      ,11994.7
832.1404
River Rch & RM=BeardRn,Main      ,9561.1
914.9763
River Rch & RM=BeardRn,Main      ,9561.1
1570.540
River Rch & RM=BeardRn,Main      ,7993.2
1600.600
River Rch & RM=BeardRn,Main      ,5961.1
1759.529
River Rch & RM=BeardRn,Main      ,291.2
1926.786
River Rch & RM=BeardRn,Main      ,56.5
1942.092
Boundary for River Rch & Prof#=BeardRn,Main      ,1
Up Type=0
Dn Type=3
Dn Slope=0.003824

--- BeardRn.g01 (geometry) ---

Geom Title=USGS 3m DEM
Program Version=4.00

River Reach=BeardRn         ,Main
Reach XY= 30
     1775794.243      274320.111     1775491.459      274143.394
     1775483.695      273989.516     1774869.906      273980.607
      1774622.85      273685.958     1774088.718      273978.982
      1773385.52      273582.262     1772243.012        273437.8
      1772018.78      273511.466     1771988.741      273835.819
     1771813.089      274102.247     1771784.313      274510.663
     1771905.254      274672.171     1771821.101      274998.443
     1771291.331      275211.251     1771215.194      275448.816
     1771107.175      275426.719     1771226.288      275988.061
       1770747.9      276256.941     1770736.804      276906.475
     1770444.695      277241.973     1770458.312      277733.398
     1770276.652      277823.248     1770213.604       278214.26
     1769611.121      278577.146      1769255.62      279239.909
     1768893.382      279120.687     1768711.396      279451.777
     1768378.255      279609.405     1768029.626      279577.099

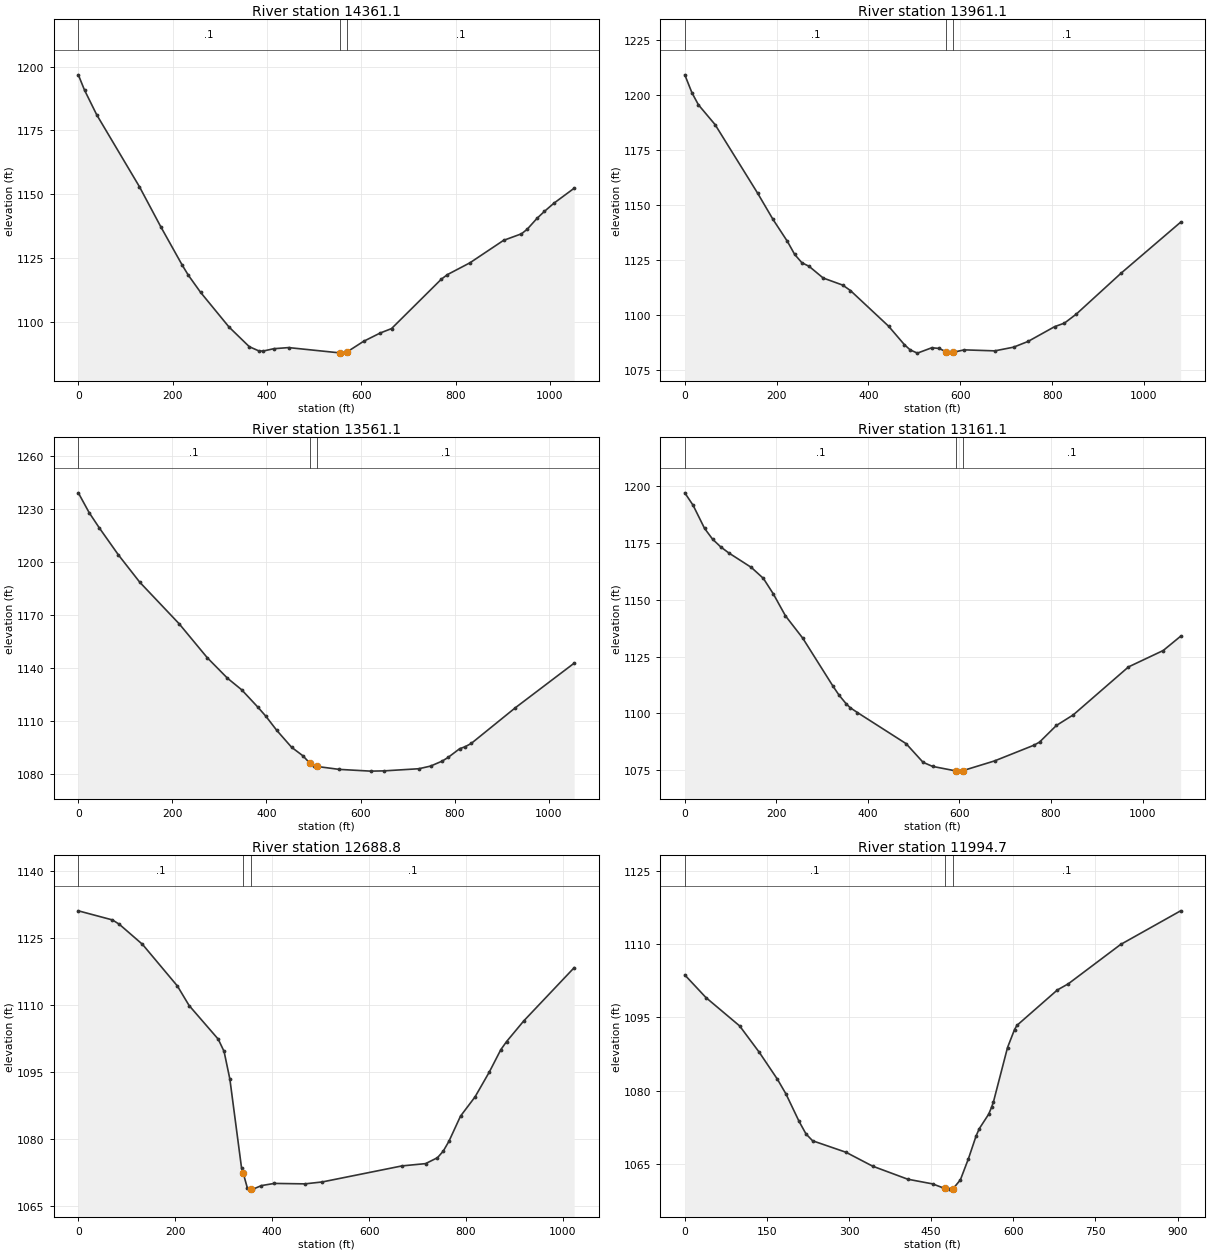
Type RM Length L Ch R = 1 ,14361.1 ,408.652,400,408.527
XS GIS Cut Line= 3
      1776007.95      273805.151     1775784.245      274320.324
     1775794.648      274809.923
#Sta/Elev= 30
       0 1196.77    13.1 1190.79      39  1181.1   129.6 1152.91   174.7 1137.27
   220.2 1122.22   233.2 1118.25   259.1 1111.55   319.4 1097.95   362.6  1090.2
   382.6 1088.58   391.6 1088.49   414.4 1089.42   445.8 1089.86   554.1 1087.79
   556.8 1087.69   569.1 1088.07   604.7  1092.3   640.3 1095.59   664.1  1097.3
   769.9  1116.7   782.8 1118.48   830.3 1123.08   901.6 1131.88   939.7 1134.46
   951.8 1136.24   972.8 1140.55   988.2 1143.22  1008.4 1146.44  1051.4 1152.32
#Mann= 3 , 0 , 0
       0      .1       0   554.1    .045       0   569.1      .1       0
Bank Sta=554.1,569.1
XS Rating Curve= 0 ,0
Exp/Cntr=0.3,0.1

Type RM Length L Ch R = 1 ,13961.1 ,384.834,400,383.853
XS GIS Cut Line= 3
     1775922.946      273750.219     1775487.018      274128.711
      1775199.55      274540.993
#Sta/Elev= 30
       0 1208.98    15.7 1200.78    29.7 1195.38      66 1186.39   158.7 1155.27
   192.1  1143.4   223.6 1133.38   239.3 1127.52     255 1123.74   270.7 1122.12
   301.4 1116.81   343.9  1113.6   360.7 1111.14   443.7 1094.99   478.5 1086.53
   490.9 1084.21   506.6 1082.74     538 1085.18   553.8 1084.87   569.8 1083.28
   584.8 1083.13   608.5 1084.22   675.2 1083.77     716 1085.44   747.6 1088.04
   805.5 1094.75   826.9 1096.36   852.5 1100.41   950.2    1119  1079.9 1142.13
#Mann= 3 , 0 , 0
       0      .1       0   569.8    .045       0   584.8      .1       0
Bank Sta=569.8,584.8
XS Rating Curve= 0 ,0
Exp/Cntr=0.3,0.1

Type RM Length L Ch R = 1 ,13561.1 ,392.867,400,396.741
XS GIS Cut Line= 3
     1775346.445      273485.698     1775285.687      273981.768
     1775130.448      274513.964
#Sta/Elev= 30
       0 1239.28      23 1228.06    44.4 1219.49    85.3 1204.07   130.6 1188.63
   214.4 1165.06   274.2 1145.82   317.1 1134.22   347.2 1127.69   381.8 1117.81
   398.9 1112.62   421.8 1104.71   453.4  1095.1   477.5 1090.25   489.5 1086.86
   492.3  1086.4   501.5 1084.53   507.3 1084.22   554.2 1082.57   621.2 1081.57
   649.9 1081.71   724.1 1082.93   748.9 1084.43   773.6 1087.25     786  1089.3
   810.7 1094.26   822.3 1095.38   835.4 1097.26   929.2 1117.49  1054.2 1142.74
#Mann= 3 , 0 , 0
       0      .1       0   492.3    .045       0   507.3      .1       0
Bank Sta=492.3,507.3
XS Rating Curve= 0 ,0
Exp/Cntr=0.3,0.1

Type RM Length L Ch R = 1 ,13161.1 ,479.848,472.313,467.209
XS GIS Cut Line= 3
     1775178.348      273456.667     1774908.468      273992.614
     1774784.931      274459.491
#Sta/Elev= 30
       0 1197.05    18.2 1191.54    43.1 1181.42    60.7 1176.65    78.4 1173.26
    96.1 1170.59   145.3 1164.22   171.7 1159.38   193.4 1152.54   219.9  1142.9
   257.5 1133.12   323.9 1111.88   337.2 1107.93   352.5  1104.2   361.3 1102.48
   377.1 1100.34   483.4 1086.65   520.5 1078.43   541.2 1076.64   592.6 1074.63
   602.8 1074.56   607.6 1074.79   676.5 1079.05   762.5 1085.96   774.8 1087.33
   811.6 1094.65   848.5 1099.32   969.1 1120.43    1045 1127.65    1083 1133.93
#Mann= 3 , 0 , 0
       0      .1       0   592.6    .045       0   607.6      .1       0
Bank Sta=592.6,607.6
XS Rating Curve= 0 ,0
Exp/Cntr=0.3,0.1

Type RM Length L Ch R = 1 ,12688.8 ,692.06,694.042,702.714
XS GIS Cut Line= 3
     1774674.769      273342.059     1774621.188      273684.972
     1774585.468      274360.083
#Sta/Elev= 30
       0 1131.16    70.3 1129.12    84.4 1128.16   132.4 1123.64   204.5 1114.29
   228.6 1109.92   288.6 1102.39   300.7 1099.64   312.7 1093.41   336.7 1073.56
   340.3 1072.32   348.7 1069.02   355.3 1068.76   360.6 1068.75   377.7 1069.54
   404.4 1070.03   467.6 1069.93   503.3 1070.36     668 1073.96   716.5 1074.47
   741.1  1075.8   752.9 1077.26   764.8  1079.5   788.6 1085.12   818.6 1089.44
   848.1 1095.03   871.8 1100.03   883.7 1101.85     919 1106.46  1023.1 1118.41
#Mann= 3 , 0 , 0
       0      .1       0   340.3    .045       0   355.3      .1       0
Bank Sta=340.3,355.3
XS Rating Curve= 0 ,0
Exp/Cntr=0.3,0.1

Type RM Length L Ch R = 1 ,11994.7 ,427.6,433.645,426.999
XS GIS Cut Line= 3
     1774185.403      273506.371     1774078.242      273977.878
     1773853.205      274335.079
#Sta/Elev= 30
       0  1103.7    38.7 1099.06   100.2 1093.26   136.1 1087.85   169.2 1082.34
   184.8 1079.33   208.8  1073.7   221.4 1071.14   233.5 1069.74   294.4 1067.39
   343.1 1064.54   407.3 1061.87   452.7 1060.91   474.5 1059.99   483.5 1059.84
   489.5 1059.85   503.4 1061.74   518.2  1066.1   532.2 1070.76   537.9 1072.22
   555.1 1075.19   560.3 1076.59   563.7 1077.67   589.5 1088.83   602.3 1092.52
   606.7 1093.37   680.5 1100.62   700.6 1101.89   796.1 1109.94   905.7 1116.83
#Mann= 3 , 0 , 0
       0      .1       0   474.5    .045       0   489.5      .1       0
Bank Sta=474.5,489.5
XS Rating Curve= 0 ,0
Exp/Cntr=0.3,0.1

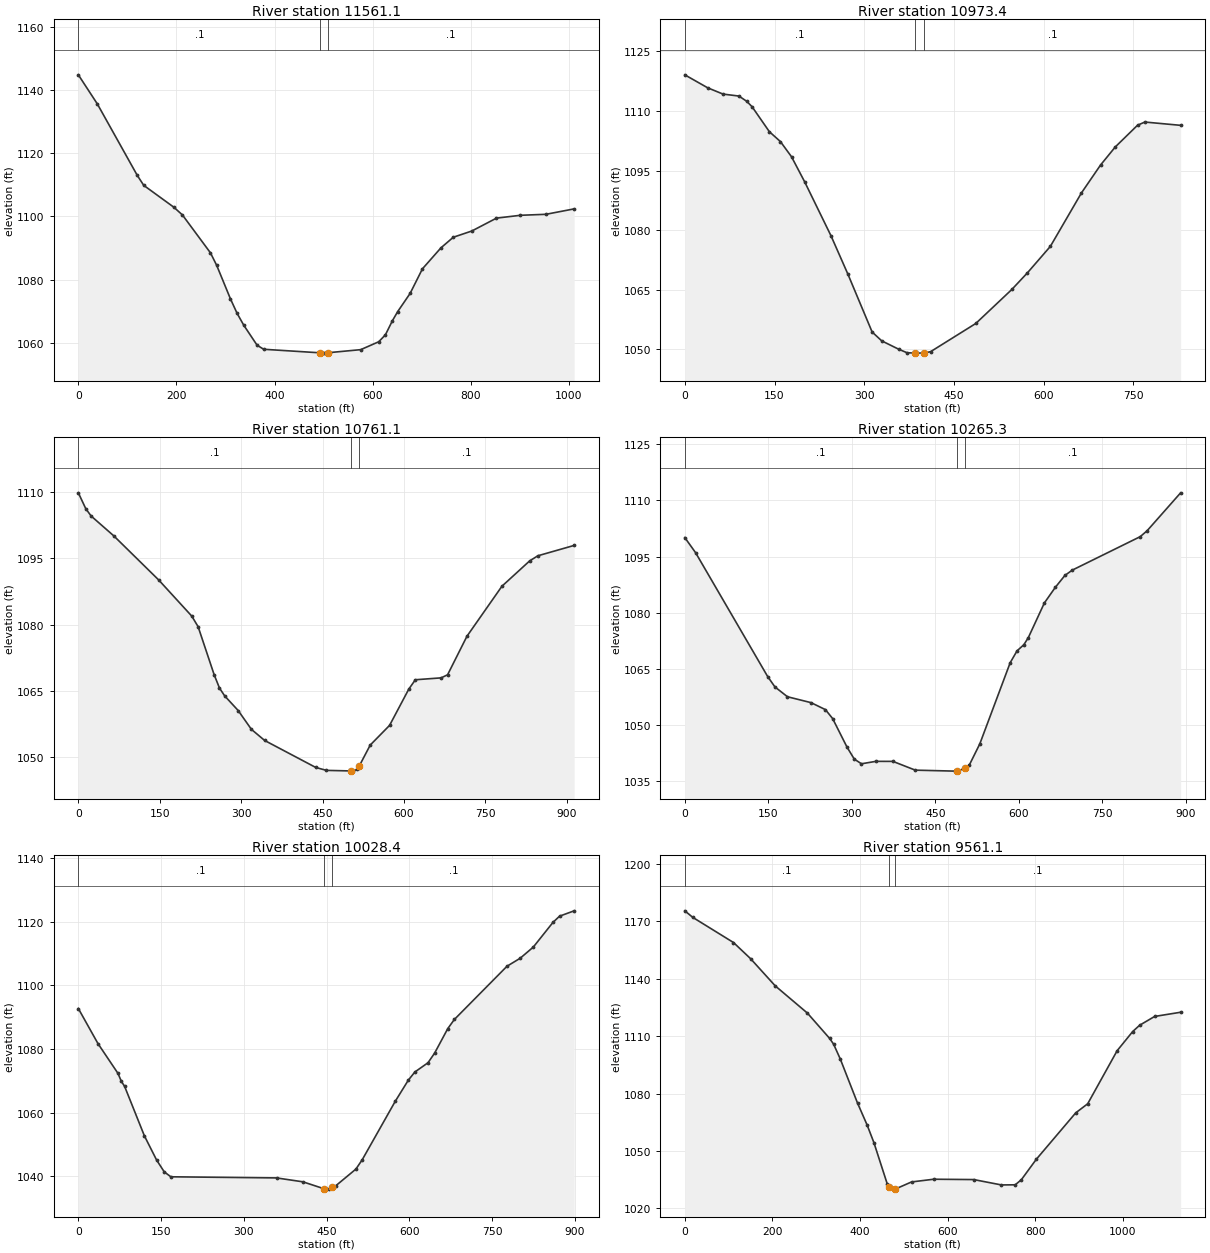
Type RM Length L Ch R = 1 ,11561.1 ,558.77,587.693,535.255
XS GIS Cut Line= 3
     1773978.357      273332.178     1773736.061      273770.628
     1773567.516      274251.549
#Sta/Elev= 30
       0 1144.86    38.7 1135.65   120.1 1113.02   133.3 1109.86   194.7 1102.93
   212.2 1100.48   269.3 1088.48   282.1 1084.48     310 1073.92   323.6 1069.32
   337.1 1065.58   364.3 1059.24   377.8 1057.95   493.4 1056.82   499.9 1056.73
   508.4 1056.85   575.5 1057.83   612.2 1060.33   625.8 1062.52   640.2 1067.02
   650.9 1069.89   676.1 1075.62   701.3 1083.43     739 1090.07   764.2 1093.43
   801.9  1095.4   852.2 1099.48     901 1100.38   952.9 1100.69  1010.5 1102.41
#Mann= 3 , 0 , 0
       0      .1       0   493.4    .045       0   508.4      .1       0
Bank Sta=493.4,508.4
XS Rating Curve= 0 ,0
Exp/Cntr=0.3,0.1

Type RM Length L Ch R = 1 ,10973.4 ,220.664,212.307,208.706
XS GIS Cut Line= 3
     1773535.295      273267.046     1773324.547      273595.672
     1773203.098       274017.17
#Sta/Elev= 30
       0 1119.11    38.3 1115.84      64 1114.26    90.5 1113.77   103.5 1112.45
   112.5 1111.08   141.4  1104.8   159.9 1102.31   178.4  1098.5   200.4 1092.19
   244.4 1078.62   272.8 1068.92   313.2  1054.4   329.2 1052.17   357.4 1050.08
   371.5 1049.18   385.4 1049.09   385.6 1049.08   400.4 1049.12   410.9 1049.44
   486.5 1056.54   546.8  1065.1   572.9 1069.29   611.2 1075.94   663.2  1089.4
   695.1 1096.41   719.8 1100.97   756.9 1106.42   769.2 1107.23     829  1106.4
#Mann= 3 , 0 , 0
       0      .1       0   385.4    .045       0   400.4      .1       0
Bank Sta=385.4,400.4
XS Rating Curve= 0 ,0
Exp/Cntr=0.3,0.1

Type RM Length L Ch R = 1 ,10761.1 ,493.07,495.784,500.247
XS GIS Cut Line= 3
     1773240.403      273067.756     1773121.965      273563.926
     1773106.654      273967.162
#Sta/Elev= 30
       0 1109.86    13.7 1106.27    23.6  1104.6    65.2 1100.12     148 1090.12
     209 1081.92   220.7 1079.52   250.3 1068.62   260.1  1065.6   269.8 1063.81
   294.5 1060.52   318.9 1056.25   343.3 1053.73   437.5 1047.61   457.2 1046.95
   502.6 1046.82   506.5 1046.78   514.1 1047.18   517.6 1047.93   537.8 1052.68
   573.5 1057.15   608.9 1065.37     621 1067.49   668.5 1067.92   680.4 1068.62
   716.1 1077.36   780.6  1088.7   831.6 1094.43   846.7 1095.59   913.6 1097.94
#Mann= 3 , 0 , 0
       0      .1       0   502.6    .045       0   517.6      .1       0
Bank Sta=502.6,517.6
XS Rating Curve= 0 ,0
Exp/Cntr=0.3,0.1

Type RM Length L Ch R = 1 ,10265.3 ,244,236.903,228.995
XS GIS Cut Line= 3
     1772856.612      273027.721     1772660.152      273477.795
     1772556.563      273863.573
#Sta/Elev= 30
       0 1100.06    19.4 1096.02   148.9 1062.95   161.9 1060.19   184.4 1057.57
   226.7    1056   252.6 1054.13   265.5 1051.75   291.4 1044.11   304.4 1040.93
   317.3 1039.68   343.2 1040.33   373.8 1040.32     414 1037.98   485.7 1037.72
   488.6 1037.75   503.6 1038.45   510.6 1039.23   529.8 1044.98   584.4 1066.66
   596.7 1069.82     609 1071.47     617 1073.36   645.8 1082.61   665.4 1086.76
   682.7 1089.96   695.9 1091.37   817.9  1100.3   830.2 1101.86   890.5    1112
#Mann= 3 , 0 , 0
       0      .1       0   488.6    .045       0   503.6      .1       0
Bank Sta=488.6,503.6
XS Rating Curve= 0 ,0
Exp/Cntr=0.3,0.1

Type RM Length L Ch R = 1 ,10028.4 ,492.828,467.313,442.429
XS GIS Cut Line= 3
     1772481.551      273009.861     1772424.398      273452.791
     1772463.691      273902.865
#Sta/Elev= 30
       0 1092.71    35.6 1081.69    71.8 1072.36      78 1069.83    83.8  1068.3
   119.7 1052.75   141.7  1045.2   155.6 1041.46   167.6  1039.9   359.1 1039.55
     407 1038.32   445.3 1036.14   454.9 1036.03   460.3 1036.55   466.8 1037.13
     503 1042.33   514.5 1045.28   574.1 1063.55   597.9 1070.22   609.8 1072.79
   633.6 1075.69   645.6 1078.72   669.4  1086.4   681.3 1089.26   776.7 1105.97
   800.5 1108.47   824.3 1111.97   860.1 1119.75     872 1121.69   898.4 1123.36
#Mann= 3 , 0 , 0
       0      .1       0   445.3    .045       0   460.3      .1       0
Bank Sta=445.3,460.3
XS Rating Curve= 0 ,0
Exp/Cntr=0.3,0.1

Type RM Length L Ch R = 1 ,9561.1  ,405.367,400,390.674
XS GIS Cut Line= 3
     1771643.904      273223.793     1772010.932      273522.585
     1772445.131      274018.205
#Sta/Elev= 30
       0 1175.43    18.3    1172   111.2 1158.87   150.1 1150.47   206.5 1136.24
     280 1122.01   330.6 1108.82   339.8  1105.8   355.1 1098.01   394.6 1074.92
   416.3 1063.59   431.9 1054.33   462.2 1032.86   465.8  1031.4   478.3 1030.08
   480.8 1030.13   517.7 1033.83   568.4 1035.25   659.8 1035.07   722.9 1032.27
   754.5 1032.33   768.5 1034.99   802.6 1045.65   892.7 1069.92     920 1074.66
   987.3  1102.4  1022.8 1112.39  1038.6 1115.67  1072.9 1120.27  1132.2 1122.46
#Mann= 3 , 0 , 0
       0      .1       0   465.8    .045       0   480.8      .1       0
Bank Sta=465.8,480.8
XS Rating Curve= 0 ,0
Exp/Cntr=0.3,0.1

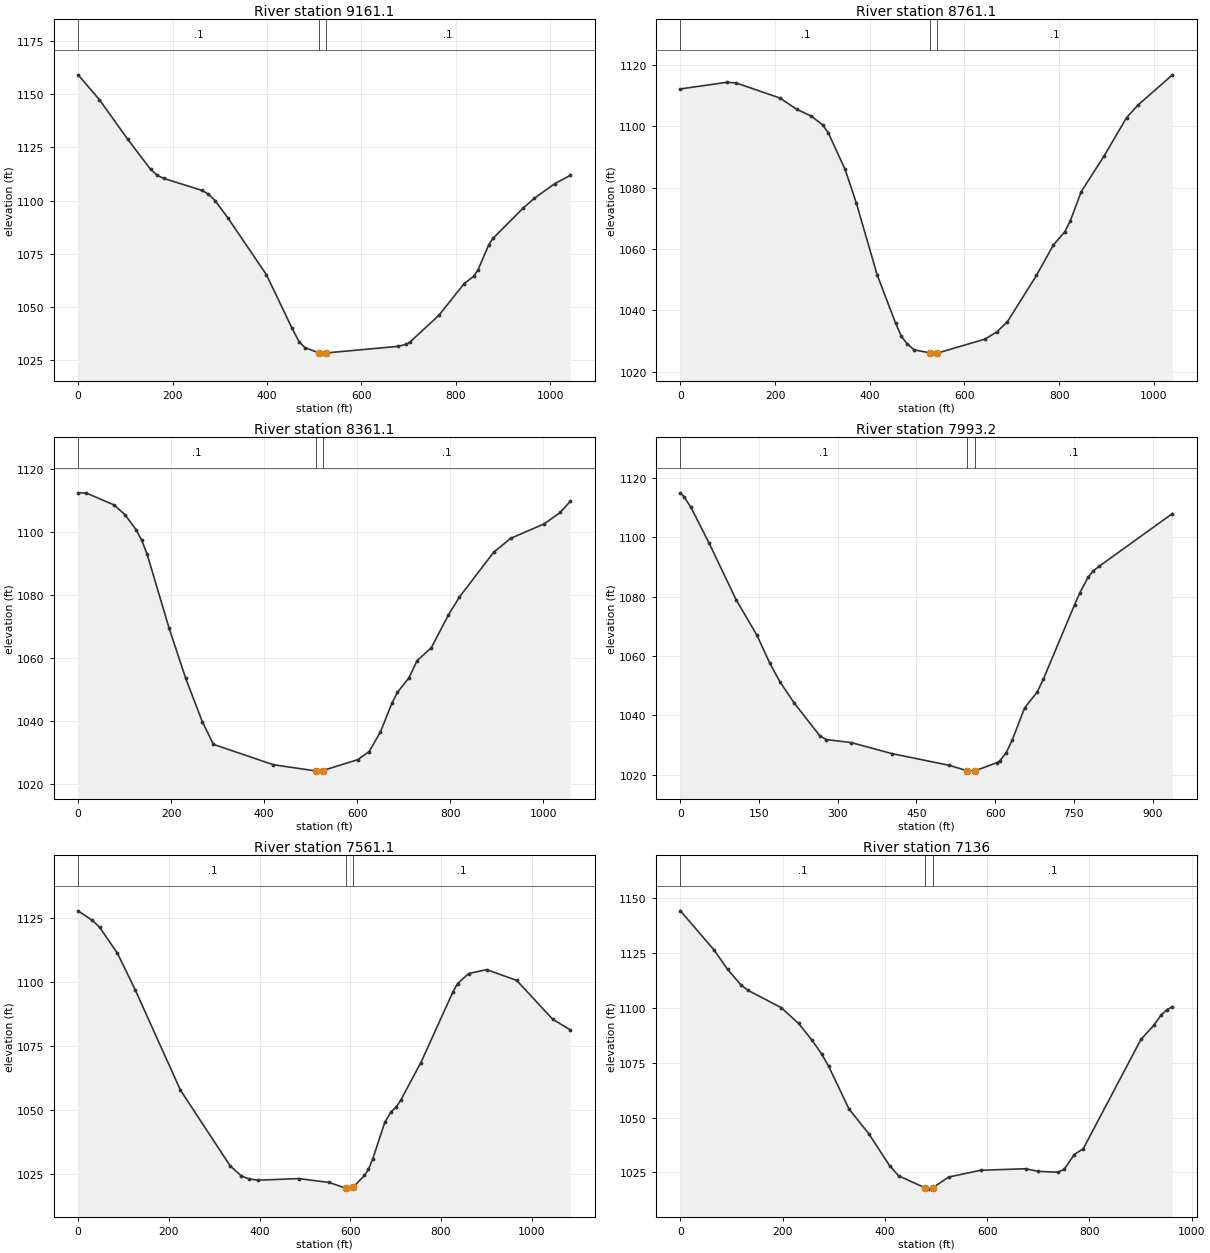
Type RM Length L Ch R = 1 ,9161.1  ,393.851,400,395.642
XS GIS Cut Line= 3
     1771476.198      273623.406     1771927.451      273875.965
     1772386.944      274129.584
#Sta/Elev= 30
       0 1159.04    45.2 1147.33   105.1 1128.74   153.7  1114.6   167.6 1111.86
   181.2  1110.4   262.8 1104.73     276 1102.96   290.1 1099.96   317.3  1091.8
   398.9 1065.12   453.3 1039.91   467.9 1033.73   480.5 1030.92   509.6 1028.49
   518.4 1028.34   524.6 1028.42   677.6 1031.52     695 1032.52   703.8 1033.75
   764.1 1046.13   817.4 1060.95   837.8 1064.44   846.8 1067.43   869.8 1079.32
   878.5 1082.24   941.7  1096.3   965.9 1101.03  1009.6 1107.96    1042 1111.79
#Mann= 3 , 0 , 0
       0      .1       0   509.6    .045       0   524.6      .1       0
Bank Sta=509.6,524.6
XS Rating Curve= 0 ,0
Exp/Cntr=0.3,0.1

Type RM Length L Ch R = 1 ,8761.1  ,411.316,400,392.49
XS GIS Cut Line= 3
     1771322.018      274190.601     1771857.543      274188.628
     1772360.211      274222.504
#Sta/Elev= 30
       0 1112.17    98.6 1114.35   117.4 1114.13     210 1109.22   245.5 1105.55
   276.7 1103.29   300.4 1100.46   312.3 1097.89   347.9 1085.92   371.7 1074.94
   415.4 1051.66   454.8 1035.71   466.7 1031.54   478.5 1029.15   493.9 1027.12
     528  1026.1   537.9 1026.05     543 1026.07   643.8 1030.64   668.8 1033.04
   690.7 1036.28   752.1  1051.4   787.8 1061.31   811.6 1065.55   823.5 1069.13
   846.7 1078.72   894.9 1090.31   942.5 1102.84   966.3 1106.89  1039.3 1116.77
#Mann= 3 , 0 , 0
       0      .1       0     528    .045       0     543      .1       0
Bank Sta=528,543
XS Rating Curve= 0 ,0
Exp/Cntr=0.3,0.1

Type RM Length L Ch R = 1 ,8361.1  ,370.313,367.827,371.949
XS GIS Cut Line= 3
       1771296.2       274535.62     1771814.565      274544.902
     1772341.297      274430.079
#Sta/Elev= 30
       0 1112.41    17.6 1112.34    76.9  1108.6   100.7 1105.47   124.4 1100.75
   136.3 1097.47   148.2    1093   195.7 1069.44   231.3 1053.57   266.9 1039.88
   290.7 1032.68   419.6 1026.22   510.9 1024.25   516.3 1024.19   525.9 1024.38
   601.3 1027.84   625.6  1030.4   649.9 1036.64   674.2 1045.65   686.4 1049.17
   710.7  1053.7   728.6 1059.23     759 1063.28   795.7 1073.63   818.8 1079.23
   892.9 1093.53   929.4 1097.95  1002.3 1102.61  1036.4 1106.21  1057.6  1109.7
#Mann= 3 , 0 , 0
       0      .1       0   510.9    .045       0   525.9      .1       0
Bank Sta=510.9,525.9
XS Rating Curve= 0 ,0
Exp/Cntr=0.3,0.1

Type RM Length L Ch R = 1 ,7993.2  ,419.445,432.173,455.327
XS GIS Cut Line= 3
     1771306.357      274695.853     1771845.732      274842.306
     1772224.366      274860.166
#Sta/Elev= 30
       0    1115     7.7 1113.47      20 1110.11    54.4 1098.16   106.1 1079.01
   145.7 1067.08   170.5 1057.56   189.8 1051.33   216.8 1044.21     266 1033.08
   278.3 1031.86   325.3 1030.87   402.7 1027.16   512.1  1023.2   547.2 1021.34
     549 1021.23   562.2 1021.37   602.6 1024.04   608.8 1024.68   620.6 1027.28
   632.5 1031.66   656.3 1042.56   680.1 1047.87     692 1052.27   751.4 1077.29
   761.5 1081.31   777.6  1086.7     787 1088.68   798.9 1090.32     938 1108.02
#Mann= 3 , 0 , 0
       0      .1       0   547.2    .045       0   562.2      .1       0
Bank Sta=547.2,562.2
XS Rating Curve= 0 ,0
Exp/Cntr=0.3,0.1

Type RM Length L Ch R = 1 ,7561.1  ,435.279,425.015,407.054
XS GIS Cut Line= 3
     1771221.504      274707.518     1771612.979      275161.029
     1771826.593       275597.15
#Sta/Elev= 30
       0 1127.79    31.6 1124.02    47.2 1121.38    86.7 1111.17   125.7 1096.93
   225.5 1057.67   334.9 1028.08   360.1 1024.01   376.6 1022.94   395.6 1022.41
   486.3 1023.03   553.7 1021.51   591.6 1019.17   595.4 1018.91   606.6 1019.76
   631.2 1024.26     640 1026.65   649.5 1030.75     676 1045.02   689.2 1048.99
   701.6 1051.13     711 1053.68   755.6 1068.44   826.4 1096.12   836.6 1099.33
     861 1103.27   900.7 1104.78   966.8 1100.58  1046.1 1085.39  1084.7 1081.24
#Mann= 3 , 0 , 0
       0      .1       0   591.6    .045       0   606.6      .1       0
Bank Sta=591.6,606.6
XS Rating Curve= 0 ,0
Exp/Cntr=0.3,0.1

Type RM Length L Ch R = 1 ,7136    ,979.698,990.186,998.303
XS GIS Cut Line= 3
     1770815.297      275087.588     1771243.939      275294.765
     1771704.552      275450.705
#Sta/Elev= 30
       0 1144.05    65.7 1126.27    92.1 1117.47   118.5 1110.33   131.7 1107.94
   197.6 1099.93     231 1092.82   257.7 1085.14   276.7 1078.73   289.9 1073.34
   329.5 1054.01     369 1042.44   409.2 1028.07   426.6  1023.5   479.1 1017.93
   487.1 1017.41   494.1 1018.11   524.7 1022.91   587.4    1026   675.1 1026.68
   700.2 1025.49   737.8 1025.11   750.4 1026.36   770.4 1033.16     788 1035.82
   900.8 1085.55   925.8 1091.91   940.7 1096.73   950.9 1098.94   962.4  1100.4
#Mann= 3 , 0 , 0
       0      .1       0   479.1    .045       0   494.1      .1       0
Bank Sta=479.1,494.1
XS Rating Curve= 0 ,0
Exp/Cntr=0.3,0.1

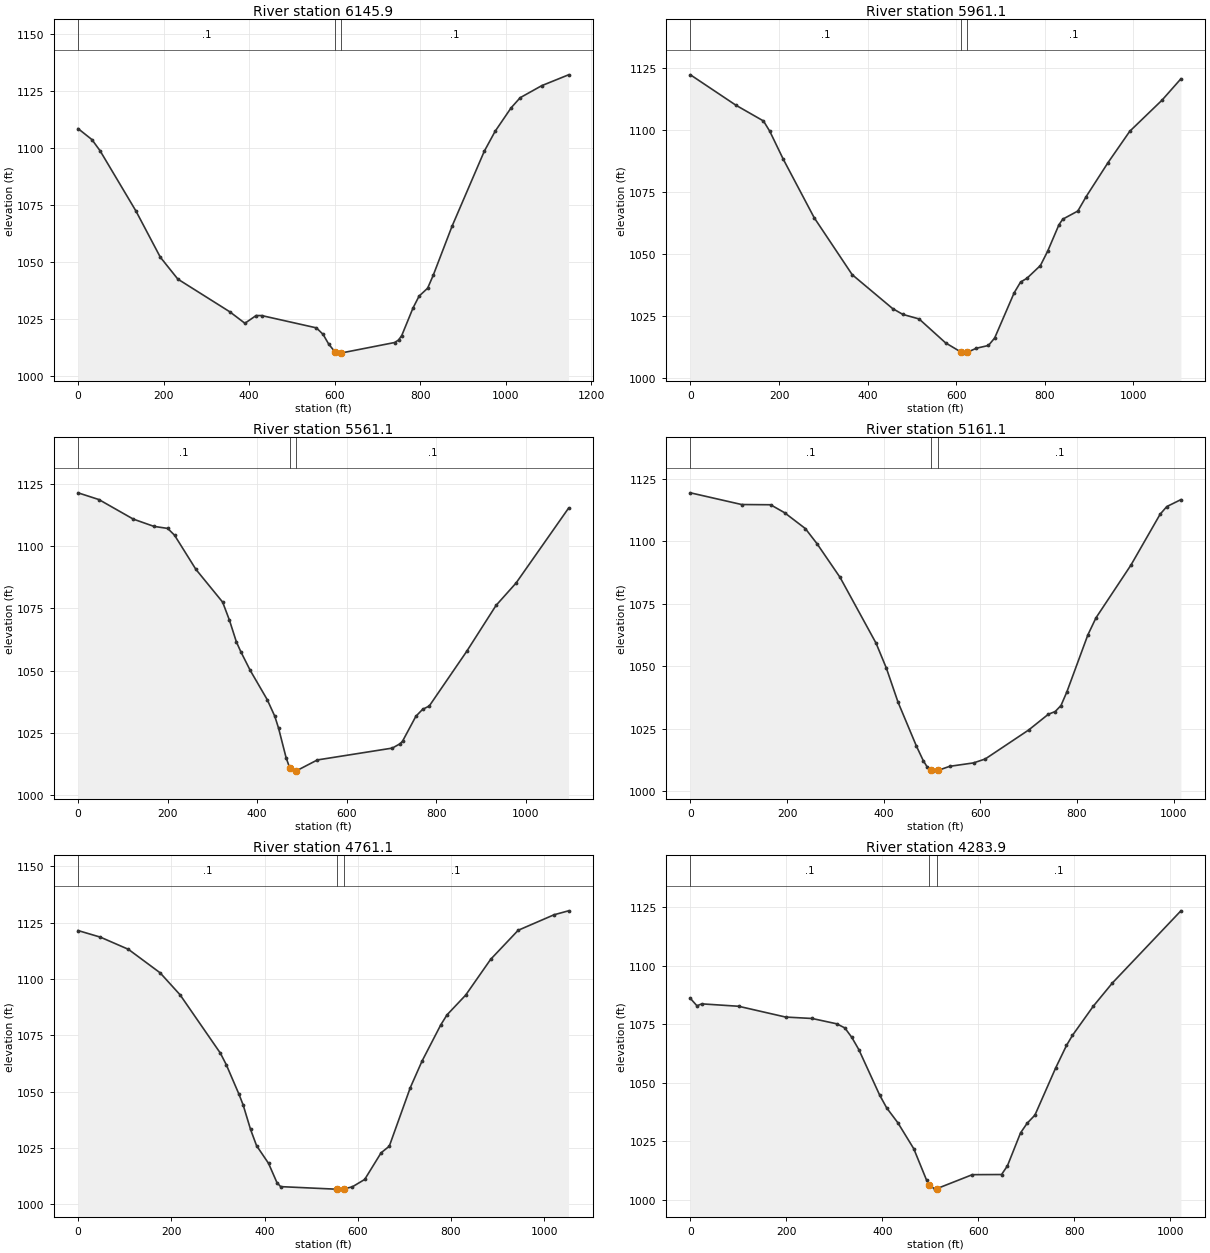
Type RM Length L Ch R = 1 ,6145.9  ,181.32,184.799,188.451
XS GIS Cut Line= 3
      1770674.11      275731.738     1771227.773      275985.351
     1771602.835      276371.129
#Sta/Elev= 30
       0 1108.52    32.4 1103.71    51.4 1098.84   135.3 1072.46   192.3 1052.24
   233.4 1042.62   354.9 1028.31   390.2 1023.29   416.3 1026.66   429.3 1026.67
   557.4 1021.28     573 1018.44     586 1014.23   600.2 1010.89   613.1 1010.22
   615.2 1010.27   740.2 1014.86   749.4 1015.94     757 1017.93   783.4 1030.01
   797.5 1035.18   817.5 1038.64   830.6  1044.3   874.5 1065.72   950.1 1098.64
   975.3 1107.32  1012.7  1117.6    1034 1122.05  1084.4 1127.32    1147 1132.06
#Mann= 3 , 0 , 0
       0      .1       0   600.2    .045       0   615.2      .1       0
Bank Sta=600.2,615.2
XS Rating Curve= 0 ,0
Exp/Cntr=0.3,0.1

Type RM Length L Ch R = 1 ,5961.1  ,394.893,400,371.363
XS GIS Cut Line= 3
     1770571.445      275742.581      1771083.96      276087.186
     1771365.458      276487.958
#Sta/Elev= 30
       0 1122.21   102.8 1109.96   164.9 1103.63   179.2 1099.46   209.2 1088.36
   279.3  1064.7   365.2 1041.73   456.4 1028.09   479.6 1025.72   516.3 1023.89
   576.2 1014.24   610.1 1010.65     619 1010.13   625.1 1010.48   645.6  1012.1
   672.8 1013.21   686.9 1016.22   730.9 1034.41   745.4 1038.75   759.9 1040.29
   790.2 1045.41   806.5 1051.15     832 1061.81   840.6 1064.07   874.7 1067.36
   893.5 1073.17   942.8 1086.84     992 1099.49  1064.6 1111.97  1107.4  1120.6
#Mann= 3 , 0 , 0
       0      .1       0   610.1    .045       0   625.1      .1       0
Bank Sta=610.1,625.1
XS Rating Curve= 0 ,0
Exp/Cntr=0.3,0.1

Type RM Length L Ch R = 1 ,5561.1  ,417.376,400,400.377
XS GIS Cut Line= 3
     1770482.017      275823.391     1770786.586      276194.509
     1771276.461      276566.844
#Sta/Elev= 30
       0  1121.4    46.5  1118.7   123.3 1110.85   169.5 1107.92   200.1 1107.11
   215.4  1104.4   263.1 1090.68   322.9  1077.5   337.9 1070.35   353.6 1061.53
   363.4 1057.62   384.4 1050.12   422.5 1038.32   439.3  1031.7   447.8 1026.88
   464.7 1014.97   472.6    1011   486.1 1009.62   487.6 1009.74   534.4 1014.11
   701.8 1018.87   718.8 1020.58   724.7 1021.64   754.5 1031.65   769.4 1034.42
   784.4 1035.78   867.9  1057.7   933.5 1076.17   978.2 1085.16  1095.4 1115.22
#Mann= 3 , 0 , 0
       0      .1       0   472.6    .045       0   487.6      .1       0
Bank Sta=472.6,487.6
XS Rating Curve= 0 ,0
Exp/Cntr=0.3,0.1

Type RM Length L Ch R = 1 ,5161.1  ,385.494,400,407.966
XS GIS Cut Line= 3
     1770247.131      276509.005     1770747.017      276579.056
      1771249.28      276670.087
#Sta/Elev= 30
       0 1119.43     106 1114.75   165.9 1114.66   194.9 1111.47   237.8 1105.14
   261.8 1099.14   309.8 1085.58   384.3 1059.26   405.7 1049.24   429.7  1035.7
   467.9 1018.07   481.9 1012.33   489.6 1009.92   497.3 1008.68   501.6 1008.12
   512.3  1008.4   536.6 1010.04     586 1011.41   610.2 1012.98     700 1024.56
   740.9 1030.88     755 1031.95     767 1034.36   779.1 1039.78   822.6 1062.59
   839.4 1069.42   911.8 1090.53   972.2 1110.87     986 1113.93  1015.2 1116.71
#Mann= 3 , 0 , 0
       0      .1       0   497.3    .045       0   512.3      .1       0
Bank Sta=497.3,512.3
XS Rating Curve= 0 ,0
Exp/Cntr=0.3,0.1

Type RM Length L Ch R = 1 ,4761.1  ,473.178,477.204,472.981
XS GIS Cut Line= 3
     1770214.165      276695.164     1770730.882      276917.847
     1771165.074       277143.94
#Sta/Elev= 30
       0 1121.44    47.9 1118.51   107.9 1113.12     176 1102.69   218.8 1092.94
   305.3 1067.04   317.9 1061.95   345.3 1048.77   354.3 1043.97     370 1033.23
   382.9    1026   408.7 1018.12   426.6 1009.63   434.6 1007.81     551  1006.7
   555.2  1006.7   570.2 1006.79   588.5 1007.73   614.9 1010.99   650.1 1022.81
   667.7 1025.75   712.8 1051.75   737.9  1063.5   778.1 1079.57   791.5 1084.02
   831.6  1092.8   885.2 1108.68   944.2 1121.56  1021.3 1128.45  1052.2 1130.19
#Mann= 3 , 0 , 0
       0      .1       0   555.2    .045       0   570.2      .1       0
Bank Sta=555.2,570.2
XS Rating Curve= 0 ,0
Exp/Cntr=0.3,0.1

Type RM Length L Ch R = 1 ,4283.9  ,334.072,322.796,311.234
XS GIS Cut Line= 3
     1770041.864      276931.935     1770448.844      277219.978
     1770903.254      277480.743
#Sta/Elev= 30
       0 1086.08    13.5 1082.94    23.7 1083.76   100.4 1082.73   198.4 1078.12
   253.7 1077.51   304.8 1075.24   321.9 1073.48   336.4 1069.43     351 1064.23
   394.6 1044.72   409.1 1039.31   432.5 1032.92   465.6 1021.84   492.2 1008.46
   498.3 1006.16   510.2 1004.58   513.3 1004.75   587.7 1010.76   648.6 1010.82
   660.8 1014.51   688.2 1028.62   701.9 1032.72   718.2 1036.22   761.6 1056.45
     784 1065.99   796.4 1070.28   839.9 1082.77   879.8 1092.71  1022.5 1123.52
#Mann= 3 , 0 , 0
       0      .1       0   498.3    .045       0   513.3      .1       0
Bank Sta=498.3,513.3
XS Rating Curve= 0 ,0
Exp/Cntr=0.3,0.1

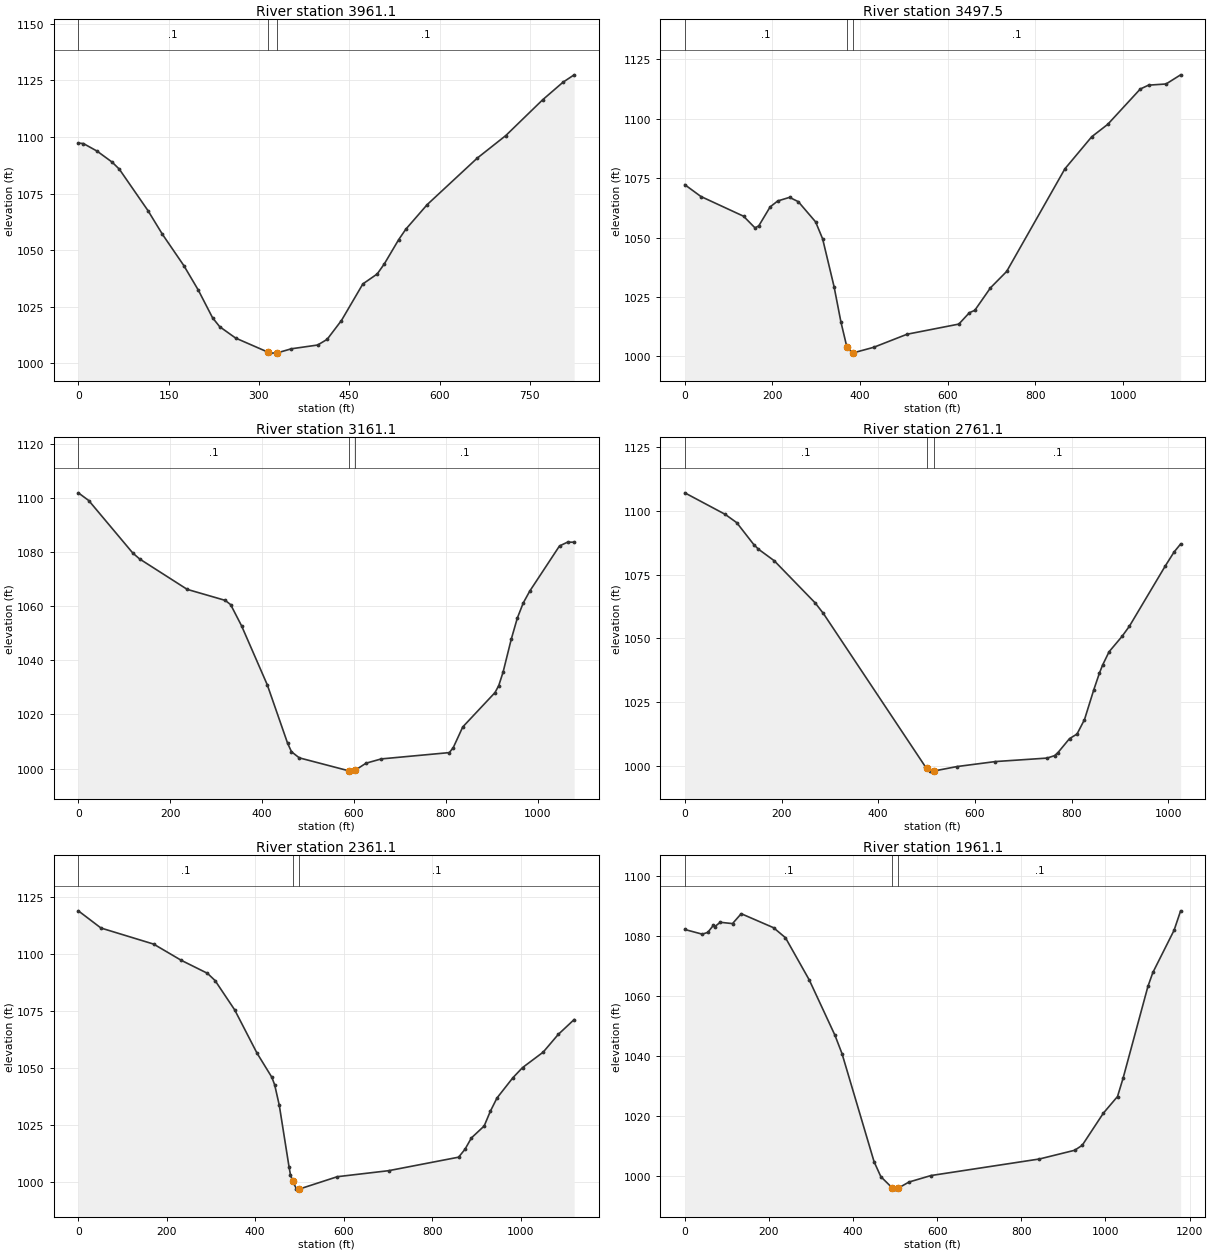
Type RM Length L Ch R = 1 ,3961.1  ,454.939,463.515,467.247
XS GIS Cut Line= 3
      1770106.16      277496.314     1770427.768      277524.084
     1770928.602      277532.531
#Sta/Elev= 30
       0 1097.31     8.5  1097.1    31.1 1093.77    56.2 1088.89    68.1 1085.79
   115.7 1067.48   139.6 1057.07   175.3 1043.19   199.2 1032.43     223 1020.15
   234.9  1016.2   261.4 1011.18   315.3 1004.94   318.3 1004.54   330.3 1004.64
     354 1006.46   397.6 1008.12   413.3 1010.62   437.1 1018.95   472.7 1035.11
   496.5  1039.5   508.3 1043.94   532.1 1054.63     544 1059.26   579.6 1070.15
   662.7 1090.67   710.2 1100.65   771.3 1116.42   805.2  1124.2   823.7 1127.46
#Mann= 3 , 0 , 0
       0      .1       0   315.3    .045       0   330.3      .1       0
Bank Sta=315.3,330.3
XS Rating Curve= 0 ,0
Exp/Cntr=0.3,0.1

Type RM Length L Ch R = 1 ,3497.5  ,333.127,336.485,342.873
XS GIS Cut Line= 3
     1769952.563      277653.482     1770270.473      277846.371
     1771013.452       278003.54
#Sta/Elev= 30
       0 1072.24    36.8 1067.27     134 1058.98   160.2 1054.06   168.8 1054.92
   194.7 1062.89     212 1065.39     239 1066.91     259 1065.09   298.5 1056.58
   314.5 1049.43   340.6 1029.31   356.2 1014.48   369.7 1003.97   382.5 1001.34
   384.7 1001.47     431 1003.79   507.2  1009.3   625.2 1013.56   649.4 1018.37
   661.6 1019.34   697.5 1028.84   734.4 1035.73   867.2 1078.91   928.5 1092.43
   964.9 1097.63  1039.3 1112.53  1058.1 1114.14  1098.1 1114.64  1131.3 1118.49
#Mann= 3 , 0 , 0
       0      .1       0   369.7    .045       0   384.7      .1       0
Bank Sta=369.7,384.7
XS Rating Curve= 0 ,0
Exp/Cntr=0.3,0.1

Type RM Length L Ch R = 1 ,3161.1  ,399.481,400,409.245
XS GIS Cut Line= 3
     1769758.091      277822.525     1770236.501       278177.49
     1770662.954      278405.434
#Sta/Elev= 30
       0 1101.81    22.7 1098.96   118.7 1079.55   133.5 1077.39     237 1066.17
   319.7 1062.11   331.6 1060.53   355.3 1052.72   411.3 1030.93   455.5 1009.38
     464 1006.22     481 1003.97   588.2  999.21   591.8  999.07   603.2  999.48
   626.3    1002   659.5 1003.58   807.5 1005.91     816  1007.7   836.8 1015.38
     907 1028.07   915.2 1030.68   924.5 1035.57   942.4 1047.78   955.6 1055.58
   968.4 1061.13   982.6 1065.52  1047.4  1082.2  1064.9  1083.6  1079.3 1083.58
#Mann= 3 , 0 , 0
       0      .1       0   588.2    .045       0   603.2      .1       0
Bank Sta=588.2,603.2
XS Rating Curve= 0 ,0
Exp/Cntr=0.3,0.1

Type RM Length L Ch R = 1 ,2761.1  ,396.472,400,391.957
XS GIS Cut Line= 3
     1769519.019      278047.694     1769921.948       278358.41
     1770253.967      278754.193
#Sta/Elev= 30
       0 1107.08    83.3 1098.67   107.4 1095.39   142.6 1086.82   152.4 1084.98
   184.9 1080.47   269.6 1063.94   286.5 1059.82   497.3  999.79   501.3  999.07
   506.6  998.15     513     998   516.3  998.09   563.2   999.8   642.4 1001.75
   749.1 1003.11   764.6 1004.06   771.7 1005.26   795.6 1010.74   811.1 1012.53
   826.6  1018.2   845.6 1029.77   857.6 1036.48     864 1039.56   877.4 1044.78
   904.1 1050.78   919.5 1054.81   993.3  1078.3  1011.8 1083.87  1025.4 1087.03
#Mann= 3 , 0 , 0
       0      .1       0   501.3    .045       0   516.3      .1       0
Bank Sta=501.3,516.3
XS Rating Curve= 0 ,0
Exp/Cntr=0.3,0.1

Type RM Length L Ch R = 1 ,2361.1  ,400.546,400,405.965
XS GIS Cut Line= 3
     1769274.013      278218.464     1769610.542      278577.772
     1770127.592      278935.836
#Sta/Elev= 30
       0 1118.83    51.2  1111.3   170.3 1104.26   232.5 1097.19   291.8 1091.49
   309.2 1088.31   353.6 1075.45     404 1056.54   437.6 1045.95     444 1042.62
   454.4  1033.7   476.5  1006.7   479.6 1003.34   484.8  1000.4   492.9  997.23
   498.9  996.98   499.8  997.02   585.6 1002.42   701.5 1005.05   859.9 1010.97
   874.4 1014.45   888.8 1019.39   917.7 1024.62   931.6 1031.04   946.6 1036.86
   982.8 1045.78  1004.4 1050.18  1051.1 1056.95  1085.2 1064.71  1121.2 1071.23
#Mann= 3 , 0 , 0
       0      .1       0   484.8    .045       0   499.8      .1       0
Bank Sta=484.8,499.8
XS Rating Curve= 0 ,0
Exp/Cntr=0.3,0.1

Type RM Length L Ch R = 1 ,1961.1  ,392.061,400,411.978
XS GIS Cut Line= 3
     1769040.874       278541.73     1769390.752      278898.601
     1769859.691      279389.482
#Sta/Elev= 30
       0 1082.04    41.4 1080.48    54.6 1081.07    67.6 1083.37    71.4    1083
    84.2 1084.44   113.4    1084   134.1  1087.3     211 1082.63   239.3 1079.29
   295.8 1065.23   356.9 1046.78   373.7 1040.65     450 1004.58     466  999.63
   492.3  995.99   499.8  995.47   507.3   995.8   532.8  997.83   585.2    1000
     843 1005.52   926.8 1008.43   944.7 1010.09     995 1020.81  1028.6 1026.35
  1041.8 1032.44  1100.8 1063.03  1112.6  1067.7    1163 1081.77  1178.6 1088.26
#Mann= 3 , 0 , 0
       0      .1       0   492.3    .045       0   507.3      .1       0
Bank Sta=492.3,507.3
XS Rating Curve= 0 ,0
Exp/Cntr=0.3,0.1

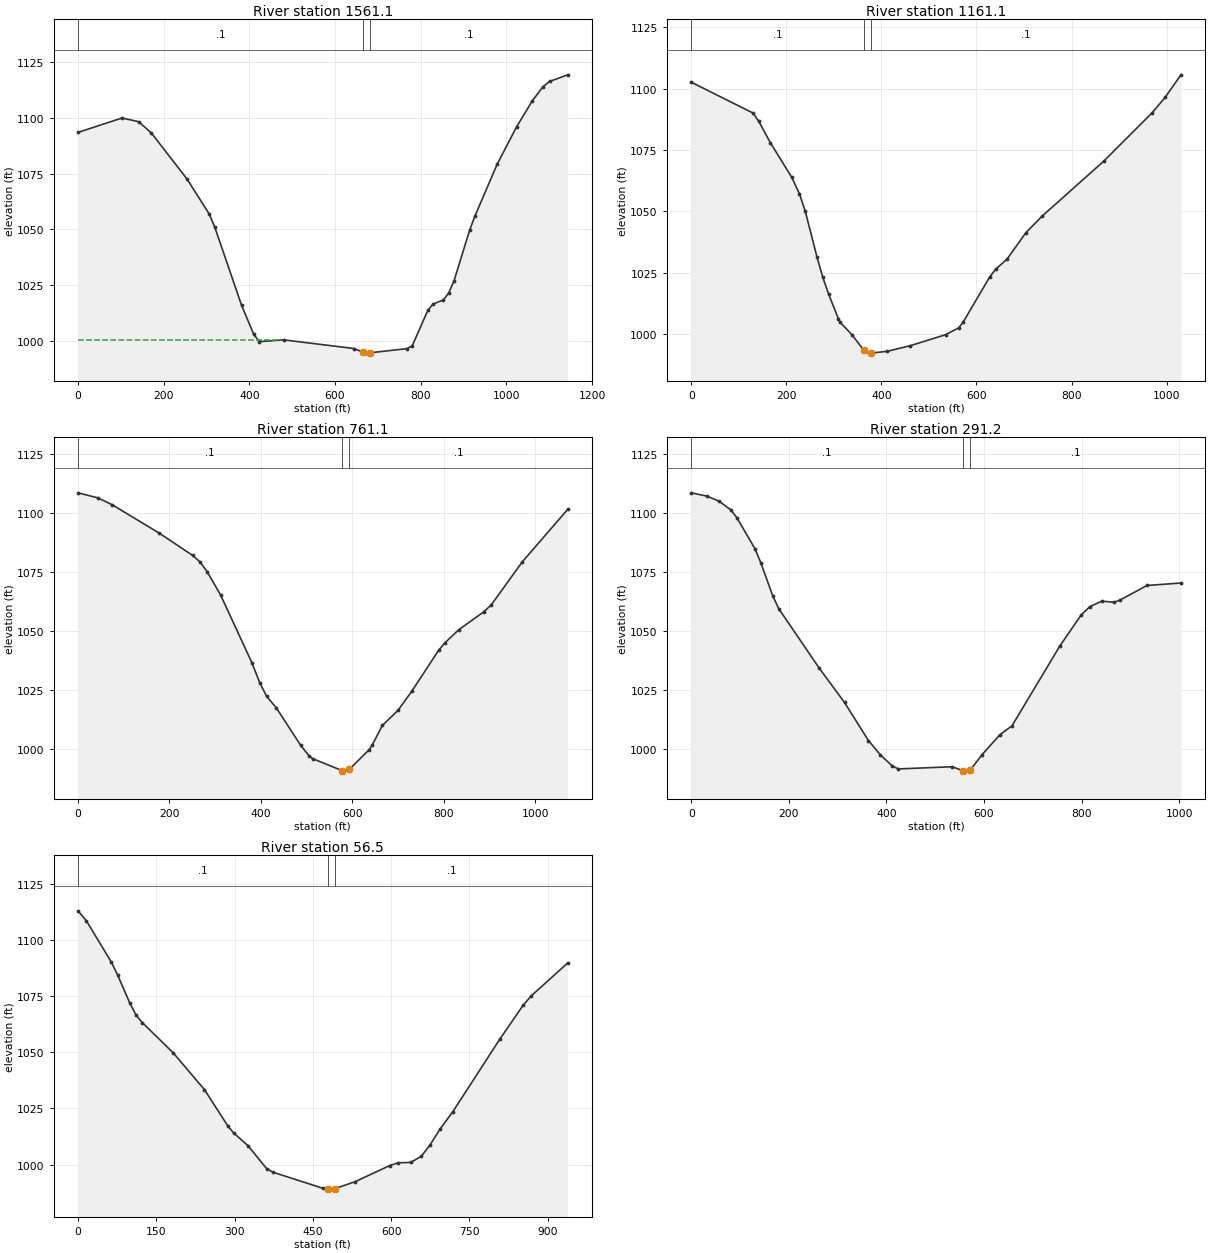
Type RM Length L Ch R = 1 ,1561.1  ,395.941,400,396.888
XS GIS Cut Line= 3
     1768964.881      278630.564     1769237.998      279245.748
     1769344.712      279703.423
#Sta/Elev= 30
       0 1093.46   102.8 1099.92   141.6 1098.25   170.9 1093.27   254.4  1072.6
   306.4 1056.89   319.4 1050.95   381.7 1016.09   410.3    1003   423.3  999.79
   480.6 1000.57   644.1   996.7   665.6  995.06   673.1  994.64   680.6  994.76
   767.8  996.66     780  997.82   816.6 1013.81   828.8 1016.62   853.1 1018.47
   865.3 1021.57   877.5 1026.85   914.1 1049.63   926.3  1055.9   978.2 1079.12
  1023.8 1095.95  1060.4 1107.58  1085.4 1113.93  1101.3 1116.31    1143 1119.24
#Mann= 3 , 0 , 0
       0      .1       0   665.6    .045       0   680.6      .1       0
#XS Ineff= 2 , 0
          474.05 1000.61
Permanent Ineff=
       F       F
Bank Sta=665.6,680.6
XS Rating Curve= 0 ,0
Exp/Cntr=0.3,0.1

Type RM Length L Ch R = 1 ,1161.1  ,410.69,400,394.678
XS GIS Cut Line= 3
     1768809.518      278760.808     1768897.826      279120.734
     1769127.063      279739.136
#Sta/Elev= 30
       0 1102.61   129.8 1090.05     142 1086.66   166.4 1077.93   211.4 1063.82
   227.6 1057.09   239.8 1049.98   264.2 1031.53   276.5 1023.19   288.7 1016.33
   309.6 1006.13   313.1 1004.76   337.6  999.76   363.1  993.33   374.4  992.18
   378.1   992.2   412.4  992.93     461  995.23   534.9  999.68   562.6 1002.49
   571.9 1004.81   627.6 1023.16   640.3 1026.37   664.2 1030.49   703.6 1041.19
   738.1 1048.03   867.5 1070.39   969.5 1090.15   996.8 1096.41  1030.1 1105.62
#Mann= 3 , 0 , 0
       0      .1       0   363.1    .045       0   378.1      .1       0
Bank Sta=363.1,378.1
XS Rating Curve= 0 ,0
Exp/Cntr=0.3,0.1

Type RM Length L Ch R = 1 ,761.1   ,458.976,469.894,478.031
XS GIS Cut Line= 3
     1768329.614      279008.745      1768720.12       279445.58
     1769001.201      279841.345
#Sta/Elev= 30
       0 1108.62    43.5 1106.48    75.4 1103.49   177.2 1091.57   250.5 1082.08
   266.5 1079.38   282.4 1075.17   311.8 1065.31   380.3 1036.56   398.1 1027.77
   412.7 1022.25   433.7 1017.37   487.2 1001.44     505  997.06   513.6  995.74
   578.4  990.64   580.8  990.46   593.4  991.16   636.3  999.42   643.3 1001.35
   665.9 1009.87     700 1016.21   730.7 1024.48   788.9 1041.71   802.2 1044.82
   832.6 1050.41   887.3 1058.02   904.3 1061.05   972.5 1079.41  1071.4 1101.55
#Mann= 3 , 0 , 0
       0      .1       0   578.4    .045       0   593.4      .1       0
Bank Sta=578.4,593.4
XS Rating Curve= 0 ,0
Exp/Cntr=0.3,0.1

Type RM Length L Ch R = 1 ,291.2   ,227.896,234.657,244.802
XS GIS Cut Line= 3
     1768164.619      279057.363     1768305.101      279609.893
     1768416.596      280028.873
#Sta/Elev= 30
       0 1108.46    32.3 1107.05    56.8 1104.93    81.3 1101.21    93.6 1097.88
   130.3  1084.9   142.6 1078.85   167.1 1064.82   179.3 1059.47   262.5 1034.26
   314.1 1019.82   363.1 1003.74   387.6  997.66   412.1  992.97   424.3  991.73
   534.6  992.65     557  990.98   559.1   990.8     572  991.31   595.9  997.73
   632.7  1006.2   657.3 1009.94   755.6 1043.73   799.2 1056.83     817 1060.37
   841.6 1062.65   866.1  1062.2   878.5 1063.09   934.1 1069.29  1003.7 1070.33
#Mann= 3 , 0 , 0
       0      .1       0     557    .045       0     572      .1       0
Bank Sta=557,572
XS Rating Curve= 0 ,0
Exp/Cntr=0.3,0.1

Type RM Length L Ch R = 1 ,56.5    ,46.108,56.513,63.786
XS GIS Cut Line= 3
     1768115.199       279120.07      1768078.94      279605.641
     1767987.293      280047.387
#Sta/Elev= 30
       0    1113    16.1 1108.55    63.8 1090.17    75.7 1084.51    99.5 1071.79
   111.4 1066.48   123.3 1063.21   182.8 1049.67   242.3 1033.36   287.5 1017.05
   298.6 1014.01   325.7 1008.43   361.4   998.2   373.3  996.63   468.5  989.51
   478.1  989.21   480.5  989.09   493.1  989.36   531.5  992.46   597.4  999.61
   613.7 1000.81   637.5 1000.98   657.6  1003.7   674.3 1008.71   693.8 1015.89
   717.9  1023.5   807.7 1055.71   852.8 1070.96   868.1 1075.08   938.1 1089.77
#Mann= 3 , 0 , 0
       0      .1       0   478.1    .045       0   493.1      .1       0
Bank Sta=478.1,493.1
XS Rating Curve= 0 ,0
Exp/Cntr=0.3,0.1

Chan Stop Cuts=-1
Use User Specified Reach Order=0